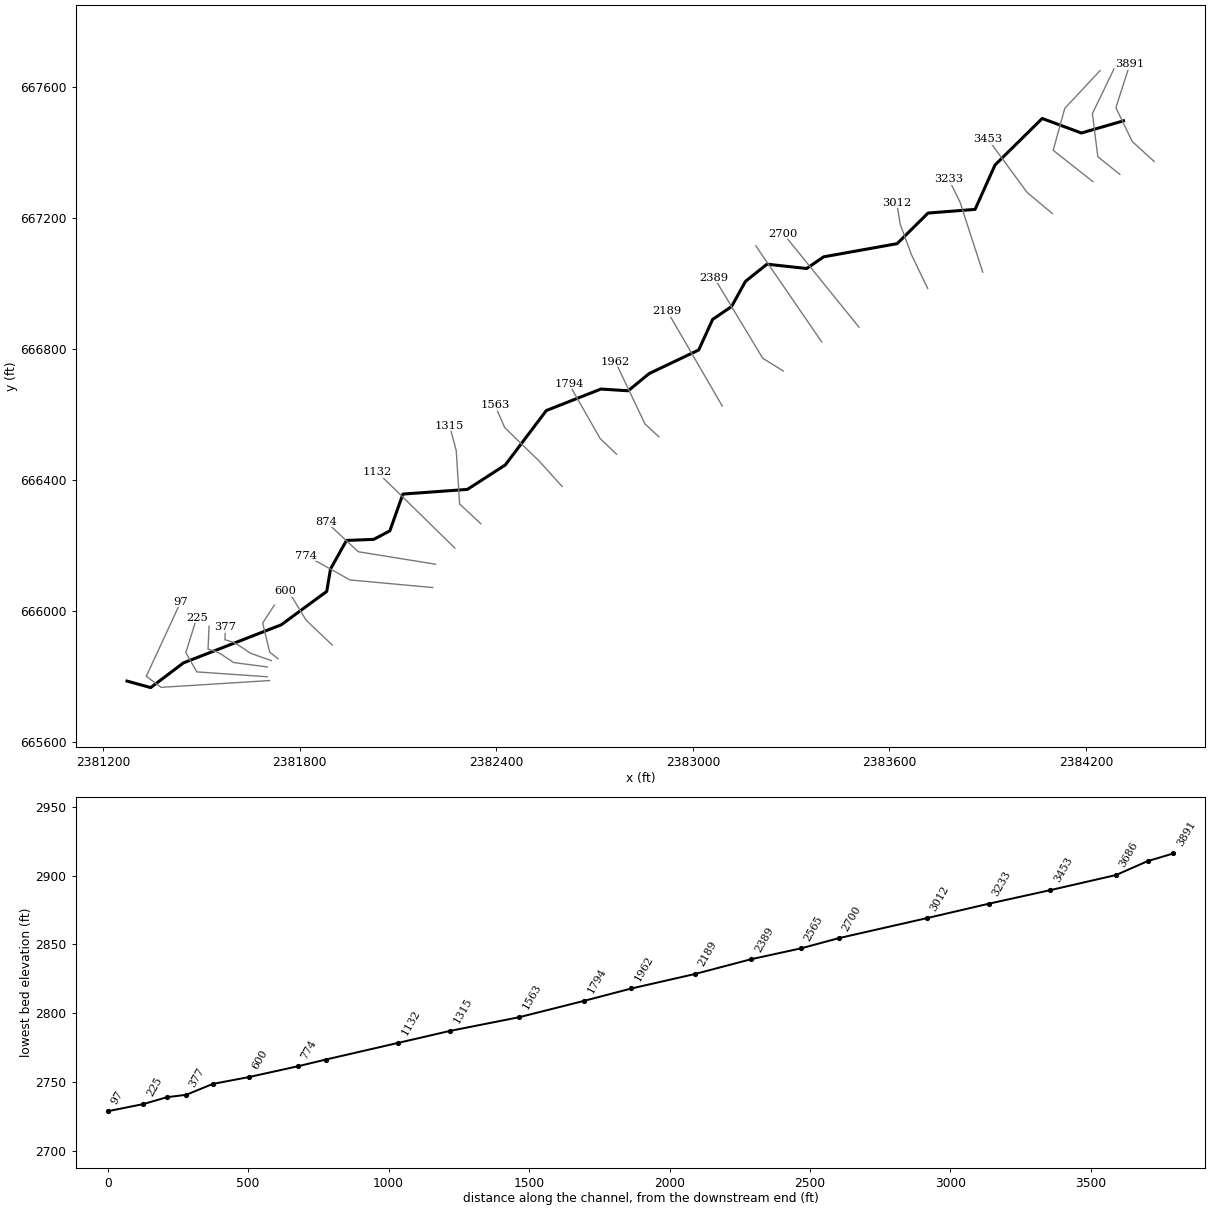
--- GNDYCK_1T1.prj (project) ---

Proj Title=GNDYCK_1T1
Current Plan=p01
Default Exp/Contr=0,0
English Units
Geom File=g01
Flow File=f01
Plan File=p01
BEGIN DESCRIPTION:
----------MODEL BY WOOD PLC 2022----------
AFH study
Randolph County, WV
HEC-RAS Version: RAS 6.2
Vertical Datum: NAVD88
Projection: NAD 1983 StatePlane West Virginia S FIPS 4702 (US Feet)
Terrain: 1-meter LIDAR (FEMA Region III 3DEP collected 2016-2018)
Land Use: 2019 NLCD
Hydrologic Method:
WV SIR2010-5033 regression equations
Additional Model Notes:
None
END DESCRIPTION:
DSS Export Rating Curves= 0
DSS Export Rating Curve Sorted= 0
DSS Export Volume Flow Curves= 0
DXF OffsetX= 0
DXF OffsetY= 0
DXF ScaleX= 0
DXF ScaleY= 0

--- GNDYCK_1T1.p01 (plan) ---

Plan Title=Floodplain
Program Version=6.20
Short Identifier=Floodplain
Geom File=g01
Flow File=f01
Subcritical Flow
K Sum by GR= 0
Std Step Tol= 0.01
Critical Tol= 0.01
Num of Std Step Trials= 20
Max Error Tol= 0.3
Flow Tol Ratio= 0.001
Split Flow NTrial= 30
Split Flow Tol= 0.02
Split Flow Ratio= 0.02
Log Output Level= 0
Friction Slope Method= 1
Unsteady Friction Slope Method= 2
Unsteady Bridges Friction Slope Method= 1
Parabolic Critical Depth
Global Vel Dist= 0 , 0 , 0
Global Log Level= 0
CheckData=True
Encroach Param=-1 ,0,0, 0
Mapping Interval=1HOUR
Computation Time Step Use Courant=        0
Computation Time Step Use Time Series=    0
Computation Time Step Count To Double=0
Computation Time Step Max Doubling=0
Computation Time Step Max Halving=0
Computation Time Step Residence Courant=0
Run HTab= 0
Run UNet= 0
Run Sediment= 0
Run PostProcess= 0
Run WQNet= 0
Run RASMapper=-1
UNET Theta= 0
UNET Theta Warmup= 0
UNET ZTol= 0
UNET ZSATol= 0
UNET MxIter= 0
UNET Max Iter WO Improvement= 0
UNET MaxInSteps= 0
UNET DtIC= 0
UNET DtMin= 0
UNET MaxCRTS= 0
UNET WFStab= 0
UNET SFStab= 0
UNET WFX= 1
UNET SFX= 1
UNET Gravity=32.174
UNET 1D Methodology=Finite Difference
UNET DSS MLevel= 1
UNET Pardiso=0
UNET DZMax Abort= 0
UNET Use Existing IB Tables= 0
UNET Froude Reduction=False
UNET Froude Limit= 0
UNET Froude Power= 0
UNET D1 Cores= 0
UNET WindReference=Eulerian
UNET WindDragFormulation=Hsu (1988)
UNET D2 Coriolis=0
UNET D2 Cores= 0
UNET D2 Theta= 1
UNET D2 Theta Warmup= 1
UNET D2 Z Tol= 0.01
UNET D2 Volume Tol= 0.01
UNET D2 Max Iterations= 20
UNET D2 Equation= 0
UNET D2 RampUpFraction=0.1
UNET D2 TimeSlices= 1
UNET D2 Turbulence Formulation=Non-Conservative (original)
UNET D2 Eddy Viscosity=0.3
UNET D2 Transverse Eddy Viscosity=0.1
UNET D2 Smagorinsky Mixing=0
UNET D2 BCVolumeCheck=0
UNET D2 Cores=0
UNET D2 SolverType=PARDISO (Direct)
UNET D2 Minimum Iterations= 2147483647
UNET D2 Maximum Iterations= 2147483647
UNET D2 Restart Number= 10
UNET D2 Relaxation Coeff=1.3
UNET D2 SOR Precondition Iterations= 10
UNET D2 ILUT Maximum Fill= 8
UNET D2 ILUT Tolerance=1E-08
UNET D1D2 MaxIter= 0
UNET D1D2 ZTol=0.01
UNET D1D2 QTol=0.1
UNET D1D2 MinQTol=1
Write IC File= 0
Write IC File at Fixed DateTime=0
Write IC File at Sim End=0
Echo Input=False
Echo Parameters=False
Echo Output=False
Write Detailed= 0
HDF Write Warmup=0
HDF Write Time Slices=0
HDF Flush=0
HDF Compression= 1
HDF Chunk Size= 1
HDF Spatial Parts= 1
HDF Use Max Rows=0
HDF Fixed Rows= 1
Calibration Method= 0
Calibration Iterations= 20
Calibration Max Change=0.05
Calibration Tolerance=0.2
Calibration Maximum=1.5
Calibration Minimum=0.5
Calibration Optimization Method= 1
WQ AD Non Conservative
WQ ULTIMATE=-1
WQ Max Comp Step=1HOUR
WQ Output Interval=15MIN
WQ Output Selected Increments= 0
WQ Output face flow=0
WQ Output face velocity=0
WQ Output face area=0
WQ Output face dispersion=0
WQ Output cell volume=0
WQ Output cell surface area=0
WQ Output cell continuity=0
WQ Output cumulative cell continuity=0
WQ Output face conc=0
WQ Output face dconc_dx=0
WQ Output face courant=0
WQ Output face peclet=0
WQ Output face adv mass=0
WQ Output face disp mass=0
WQ Output cell mass=0
WQ Output cell source sink temp=0
WQ Output nsm pathways=0
WQ Output nsm derived pathways=0
WQ Create Restart=0
WQ Fixed Restart=0
WQ System Summary=0
WQ Write To DSS=0
Sorting and Armoring Iterations= 10
XS Update Threshold= 0.02
Bed Roughness Predictor= 0
Hydraulics Update Threshold= 0.02
Energy Slope Method= 1
Volume Change Method= 1
Sediment Retention Method= 0
Sediment TS Multiplier= 1
Warm Up Method= 0
XS Weighting Method= 0
Number of US Weighted Cross Sections= 1
Number of DS Weighted Cross Sections= 1
Upstream XS Weight=0
Main XS Weight=1
Downstream XS Weight=0
Number of DS XS's Weighted with US Boundary= 1
Upstream Boundary Weight= 1
Weight of XSs Associated with US Boundary= 0
Number of US XS's Weighted with DS Boundary= 1
Downstream Boundary Weight= 0.5
Weight of XSs Associated with DS Boundary= 0.5
Percentile Method= 0
Sediment Output Level= 3
Mass or Volume Output= 0
Output Increment Type= 1
Profile and TS Output Increment= 1
Transport Output Increment 1
XS Output Flag= 0
XS Output Increment= 10
Read HDF5 Sediment Hotstart= 0
Sediment Hotstart Type= 0
Write Gradation File= 0
Read Gradation Hotstart= 0
Write HDF5 File= 1
Write Binary Output= 1
Write DSS Sediment File= 0
DSS Sediment Output Type= 1
SV Curve= 0
Specific Gage Flag= 0
Subcell Erosion Methods= 0
Subcell Deposition Methods= 0
Advection Scheme= 1
Matrix Solver= 0
Implicit Weighting Factor= 1
Maximum Outer Loop Convergence Iterations= 5
Convergence Maximum Absolute= 0.001
Convergence RMSE= 0.0001
Grain Fractions Max Abs Error= 0.001
Max Subgrid Regions= 1
Max Subgrid Length Scale= 3.402823E+38
Initial Layer Thickness= 3.402823E+38
Min Layer Thickness= 3.402823E+38
Max Layer Thickness= 3.402823E+38
Number of Layers= 5

--- GNDYCK_1T1.f01 (steady flow) ---

Flow Title=Flow
Program Version=6.20
Number of Profiles= 1
Profile Names=P100yr
River Rch & RM=GNDYCK_1T1,Main,3891
     384
Boundary for River Rch & Prof#=GNDYCK_1T1,Main            , 1
Up Type= 0
Dn Type= 3
Dn Slope=0.04087
DSS Import GetInterval= 0
DSS Import GetPeak= 0
DSS Import FillOption= 0

--- GNDYCK_1T1.g01 (geometry) ---

Geom Title=Geometry
Program Version=6.20

River Reach=GNDYCK_1T1      ,Main
Reach XY= 30
2384314.42600003667496.7549999952384185.86656603667459.567715526
2384066.12342922667503.918061322     2383922.065      667361.772
     2383861.301667226.3560000062383717.71600002667215.159999996
2383623.30049721667121.7313302182383398.91655947667081.472392116
2383347.24517643667045.8568048642383225.98352538667059.049757991
2383160.34100001667006.5960000012383117.88501878666929.698446546
2383060.09713532666890.4285603152383017.68980507666797.192601674
2382866.36000003 666725.115000012382802.27300005666672.535999998
2382719.18637763666677.8708963692382552.34200001      666612.191
2382427.09026801666446.0512854052382311.42670456666371.445811743
2382114.62600003666357.2090000212382074.77999999666244.947999999
2382025.41000003666218.8869999952381942.41700004666215.659000009
     2381893.527666128.3260000052381882.13400003666060.123000011
2381743.24500003665958.1260000172381444.63400002665841.807000011
 2381344.7562791665766.387127799     2381272.427665786.246000022

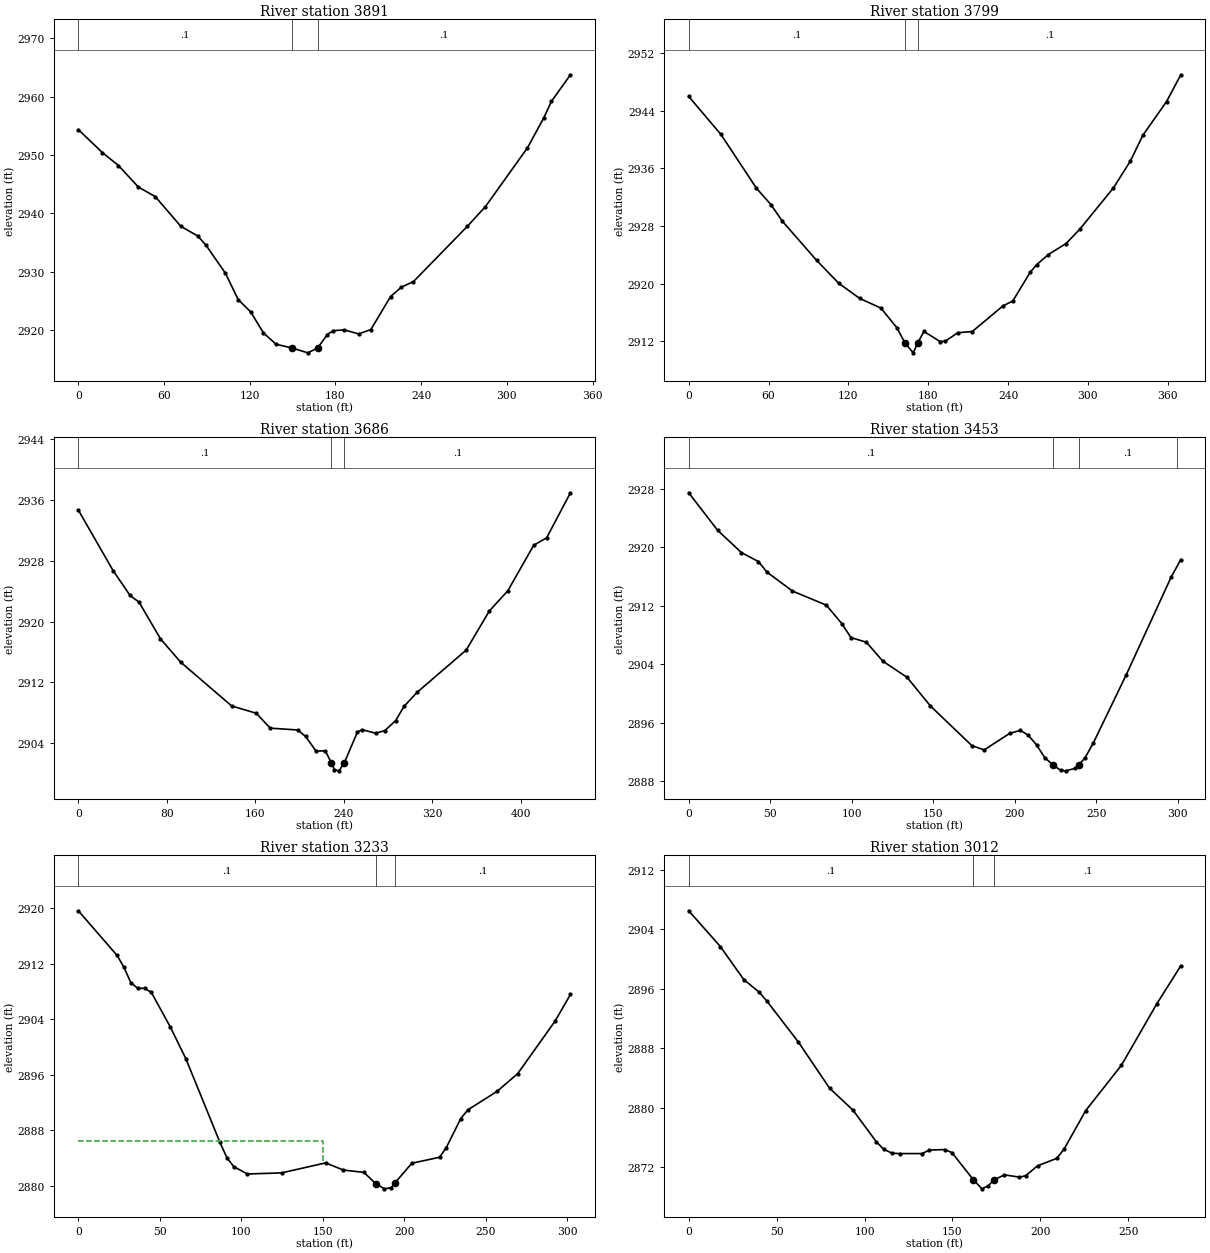
Type RM Length L Ch R = 1 ,3891    ,94,92.2,89.9
XS GIS Cut Line= 4
2384407.63833401667372.8964672622384341.12907369667433.483042985
 2384291.1003515667536.8210593222384333.88796099 667669.85950138
#Sta/Elev= 30
       0 2954.34    16.8 2950.41    28.1 2948.18      42 2944.49    53.9 2942.84
    71.7 2937.76    83.6 2936.09    89.5 2934.47     103  2929.7   111.9 2925.19
   120.7 2923.06   129.6 2919.46   138.5 2917.52  149.54 2916.88   160.7 2916.05
  167.562916.881   174.3 2919.19   178.5 2919.86   186.3 2919.98   196.3 2919.29
   204.8 2920.05   218.6 2925.71   226.2 2927.32   234.6 2928.27   272.4 2937.76
     285 2941.13   314.4  2951.2   325.9 2956.38   331.2 2959.17   344.5 2963.74
#Mann= 3, -1 ,  0
       0     0.1       0  149.54   0.045       0  167.56     0.1       0
Bank Sta=149.54,167.56
XS Rating Curve= 0 ,0
Exp/Cntr(USF)=0,0
Exp/Cntr=0.3,0.1

Type RM Length L Ch R = 1 ,3799    ,114.1,112.4,110.5
XS GIS Cut Line= 4
2384303.08796468667333.3254555672384235.99206693 667387.13503693
2384219.38417145667518.6695691532384285.15143756 667654.85431211
#Sta/Elev= 30
       0 2945.98    24.2 2940.71    50.9 2933.25    61.7 2930.99    70.4 2928.67
    96.1 2923.24   112.7 2920.07   128.4 2917.97   144.5 2916.61   156.6 2913.85
  162.342911.828   168.7 2910.41  172.182911.828   176.8 2913.38   188.9 2911.97
   192.9 2912.04   202.2  2913.2   213.1 2913.37     236  2916.9   243.6 2917.62
   256.6 2921.58   261.4 2922.63   270.2 2924.04   283.6 2925.58     294 2927.59
   319.1 2933.28   331.9 2937.02   341.3  2940.6   359.1 2945.28   369.8 2948.99
#Mann= 3, -1 ,  0
       0     0.1       0  162.34   0.045       0  172.18     0.1       0
Bank Sta=162.34,172.18
XS Rating Curve= 0 ,0
Exp/Cntr(USF)=0,0
Exp/Cntr=0.3,0.1

Type RM Length L Ch R = 1 ,3686    ,226.6,233.7,237.6
XS GIS Cut Line= 4
2384220.91443422667311.1637129752384099.73638839667406.729978755
2384135.00253683667534.6722846962384242.82979381667650.129278208
#Sta/Elev= 30
       0 2934.68    31.5  2926.7    46.8 2923.44    54.9 2922.56    74.3 2917.73
    92.6 2914.65   138.7 2908.89     161 2907.93   173.5 2905.97   198.4 2905.73
   205.5 2904.88     215 2902.94   223.3 2902.99  228.852901.392   231.6  2900.5
   235.7 2900.35   240.5 2901.39   252.3 2905.43   256.4 2905.78   268.9  2905.3
   277.2 2905.65     287 2906.97   294.6 2908.85   306.3 2910.68   350.7 2916.24
   371.7  2921.4   388.4 2924.06   411.8 2930.05   423.5 2931.03     445 2936.96
#Mann= 3, -1 ,  0
       0     0.1       0  228.85   0.045       0   240.5     0.1       0
Bank Sta=228.85,240.5
XS Rating Curve= 0 ,0
Exp/Cntr(USF)=0,0
Exp/Cntr=0.3,0.1

Type RM Length L Ch R = 1 ,3453    ,218.8,219.5,217
XS GIS Cut Line= 3
2384097.01551952667213.8124164362384020.45316586667277.655875494
2383900.71923121667440.444626103
#Sta/Elev= 30
       0 2927.48    17.7 2922.35    32.3  2919.3    42.7 2918.07      48 2916.62
    63.6 2914.03    84.4  2912.1    93.9 2909.57    99.5 2907.66     109 2907.02
     119 2904.44   133.9 2902.22   148.2 2898.31   173.6 2892.88   181.2 2892.28
   196.8 2894.54   203.4 2894.96   208.3 2894.28   213.3 2892.98   218.3 2891.24
   223.42890.227   228.2 2889.48   231.2 2889.42   236.9 2889.75  239.242890.226
   243.1 2891.22   248.1 2893.21   268.4  2902.6   295.9 2915.95   301.8 2918.34
#Mann= 4, -1 ,  0
       0     0.1       0   223.4   0.045       0  239.24     0.1       0
  299.69    0.05       0
Bank Sta=223.4,239.24
XS Rating Curve= 0 ,0
Exp/Cntr(USF)=0,0
Exp/Cntr=0.3,0.1

Type RM Length L Ch R = 1 ,3233    ,220.3,221,220.4
XS GIS Cut Line= 3
2383884.75251267 667034.561239442383815.21436408667248.644967892
2383781.45331175667317.627122783
#Sta/Elev= 30
       0 2919.62    23.8 2913.18      28 2911.48    32.2 2909.26    36.4 2908.45
    40.6 2908.44    44.8 2907.86    56.5 2902.84      66 2898.28    86.9 2886.22
    91.1 2884.05    95.3 2882.75   103.7 2881.68   124.7 2881.84   151.7 2883.28
   162.6 2882.25   175.2 2881.91  182.42  2880.3   187.8 2879.54     192  2879.7
  193.99 2880.32   204.6 2883.23   221.6 2884.09   225.7 2885.46   234.6 2889.66
     239 2890.93   256.9 2893.59   269.6 2896.16   292.5 2903.72   301.9 2907.56
#Mann= 3, -1 ,  0
       0     0.1       0  182.42   0.045       0  193.99     0.1       0
#XS Ineff= 2 , 0
          150.24 2886.42
Permanent Ineff=
       F       F
Bank Sta=182.42,193.99
XS Rating Curve= 0 ,0
Exp/Cntr(USF)=0,0
Exp/Cntr=0.3,0.1

Type RM Length L Ch R = 1 ,3012    ,311.9,312.3,312.5
XS GIS Cut Line= 4
 2383716.6058885666984.9691462522383666.79110709667088.416082721
  2383632.793303667180.5328171272383622.03553073667246.599682152
#Sta/Elev= 30
       0 2906.51      18 2901.69    31.3 2897.25    40.2 2895.52    44.6  2894.3
    62.4 2888.82    80.1 2882.61    93.4 2879.66   106.8 2875.36   110.8 2874.41
   115.6 2873.85   119.9  2873.8   132.7  2873.8   136.9 2874.27   145.5 2874.34
   149.7 2873.94  161.912870.273   166.8 2869.05   170.4 2869.47  173.722870.274
   179.6 2870.93   188.1 2870.63   191.7 2870.82   198.4 2872.15   209.4 2873.16
   213.7 2874.48   225.8 2879.59   246.1 2885.69   266.3    2894   279.9  2899.1
#Mann= 3, -1 ,  0
       0     0.1       0  161.91   0.045       0  173.72     0.1       0
Bank Sta=161.91,173.72
XS Rating Curve= 0 ,0
Exp/Cntr(USF)=0,0
Exp/Cntr=0.3,0.1

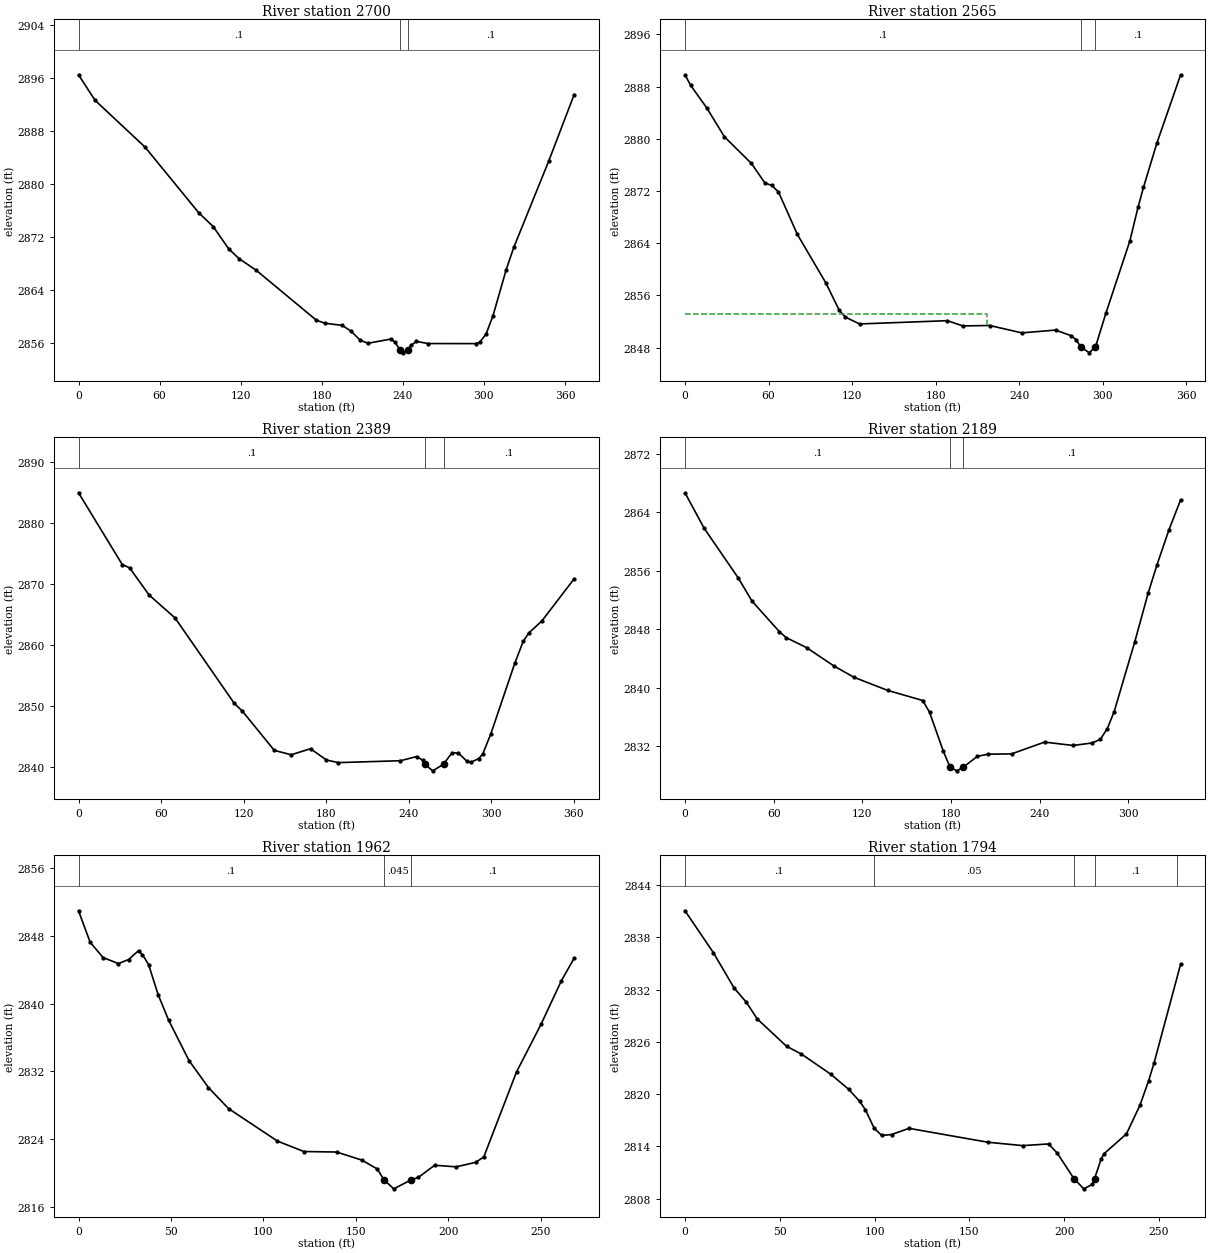
Type RM Length L Ch R = 1 ,2700    ,131.3,134.5,133.8
XS GIS Cut Line= 2
2383506.89024468666866.7126555692383276.21474016667151.890571539
#Sta/Elev= 30
       0 2896.49    12.2 2892.65    49.2  2885.6      89 2875.69    99.7 2873.61
   111.2 2870.24   118.8 2868.79   131.7    2867     176 2859.51   182.4 2859.05
   195.1 2858.73   201.5 2857.88   208.5 2856.49   214.2 2856.03   231.2 2856.67
   234.1  2856.2  237.86 2855.07   239.8 2854.59   243.62855.062     246 2855.72
   250.1 2856.31   258.7 2855.99   293.8 2855.98   296.9 2856.18   301.6 2857.42
   306.7 2860.16   316.5 2867.12   322.1 2870.47   347.9 2883.45   366.8 2893.51
#Mann= 3, -1 ,  0
       0     0.1       0  237.86   0.045       0   243.6     0.1       0
Bank Sta=237.86,243.6
XS Rating Curve= 0 ,0
Exp/Cntr(USF)=0,0
Exp/Cntr=0.3,0.1

Type RM Length L Ch R = 1 ,2565    ,176.9,176.7,175.2
XS GIS Cut Line= 2
2383392.97529224666821.8022747022383191.73434274667115.253983577
#Sta/Elev= 30
       0 2889.81     4.1 2888.19    15.6 2884.75    28.3 2880.32    47.7 2876.23
    57.4 2873.22    62.3 2872.86    67.1 2871.86    80.7 2865.34   101.1 2857.92
   110.8 2853.69   115.2 2852.67   125.3 2851.62   188.4 2852.12   199.4 2851.32
   218.8 2851.38   241.8 2850.25     266 2850.68   277.2 2849.82   280.6 2849.23
   284.3 2848.08   290.3 2847.19   294.22848.072   295.1 2848.39   302.2  2853.3
   319.4 2864.38   325.2  2869.5   329.1 2872.54   338.8 2879.38   355.8 2889.82
#Mann= 3, -1 ,  0
       0     0.1       0   284.3   0.045       0   294.2     0.1       0
#XS Ineff= 2 , 0
          216.55 2853.11
Permanent Ineff=
       F       F
Bank Sta=284.3,294.2
XS Rating Curve= 0 ,0
Exp/Cntr(USF)=0,0
Exp/Cntr=0.3,0.1

Type RM Length L Ch R = 1 ,2389    ,198.5,200.1,200.5
XS GIS Cut Line= 3
2383275.74768343666732.9081287872383212.98109853666772.030247558
2383065.09048402 667017.30095565
#Sta/Elev= 30
       0 2884.98    31.8 2873.21    37.2 2872.65    51.3 2868.21    70.2 2864.44
   113.3 2850.41   119.1 2849.16   142.4  2842.7   154.7 2841.99   168.7 2842.98
   180.3 2841.12     189  2840.7   234.1 2841.01   245.9  2841.7   250.2  2841.1
  251.992840.422   257.5 2839.35  265.392840.423   271.5 2842.31   276.2 2842.28
   282.3 2840.94   285.2 2840.74     291 2841.36   293.9  2842.1   299.8 2845.41
   317.2 2856.99   323.4 2860.63   327.5 2861.99   336.9 2863.94   360.4 2870.87
#Mann= 3, -1 ,  0
       0     0.1       0  251.99   0.045       0  265.39     0.1       0
Bank Sta=251.99,265.39
XS Rating Curve= 0 ,0
Exp/Cntr(USF)=0,0
Exp/Cntr=0.3,0.1

Type RM Length L Ch R = 1 ,2189    ,226.7,226.7,225.3
XS GIS Cut Line= 2
2383089.50691297666625.9807478972382921.25531488666916.097128853
#Sta/Elev= 30
       0 2866.65    12.9 2861.82    36.1 2854.99    45.3 2851.85    63.8 2847.67
    68.4 2846.85    82.4 2845.46   100.8 2842.96   114.5  2841.4   137.2 2839.62
   160.9 2838.24   165.5 2836.63   174.8 2831.31   179.4  2829.1     184 2828.62
  188.18  2829.1   197.9 2830.61   205.3  2830.9     221 2830.94   243.3 2832.55
   262.6 2832.09   275.5 2832.43   281.1 2832.93   285.8 2834.41   290.4  2836.7
   304.3 2846.22   313.5 2852.98   319.4 2856.79   327.4 2861.53   335.4 2865.69
#Mann= 3, -1 ,  0
       0     0.1       0   179.4   0.045       0  188.18     0.1       0
Bank Sta=179.4,188.18
XS Rating Curve= 0 ,0
Exp/Cntr(USF)=0,0
Exp/Cntr=0.3,0.1

Type RM Length L Ch R = 1 ,1962    ,167.1,168.1,166.6
XS GIS Cut Line= 3
 2382896.0670594666532.1605774852382853.55084696666571.355210824
2382763.20389553666761.349535145
#Sta/Elev= 30
       0 2850.96     6.3 2847.24    13.3 2845.43    21.6 2844.72    27.1  2845.2
    32.5 2846.25    34.6 2845.78    37.9 2844.61    43.1 2841.04    48.8 2838.01
    59.8 2833.26    70.3 2830.07    81.2 2827.58   107.6 2823.75   121.9 2822.51
   139.6 2822.45   153.3  2821.5   161.7 2820.44  165.272819.171   170.6  2818.1
  180.04 2819.17   183.9 2819.45   192.7 2820.89   204.3  2820.7   214.9 2821.23
   219.3 2821.87     237 2831.91   250.3 2837.56   261.3  2842.7   268.2 2845.36
#Mann= 3, -1 ,  0
       0     0.1       0  165.27   0.045       0  180.04     0.1       0
Bank Sta=165.27,180.04
XS Rating Curve= 0 ,0
Exp/Cntr(USF)=0,0
Exp/Cntr=0.3,0.1

Type RM Length L Ch R = 1 ,1794    ,228.7,230.6,231.6
XS GIS Cut Line= 3
2382766.92623901 666478.813740662382716.70178818666526.846050931
2382621.49867687666693.576447828
#Sta/Elev= 30
       0 2841.04      15 2836.23    25.9 2832.19    32.4 2830.54    38.1 2828.64
    53.6 2825.49    61.3 2824.62    76.8 2822.31    86.3 2820.57    92.1  2819.2
    95.2 2818.21    99.8  2816.1   103.8 2815.26     109 2815.37   118.2 2816.08
   159.7 2814.49   178.1  2814.1   191.9 2814.29   196.5 2813.21  205.172810.323
   210.4 2809.14     215 2809.66   216.1 2810.32   219.6 2812.59   221.1 2813.17
   232.9 2815.44     240 2818.71   244.6 2821.53   247.5 2823.59   261.5 2834.92
#Mann= 5, -1 ,  0
       0     0.1       0    99.5    0.05       0  205.17   0.045       0
   216.1     0.1       0   259.5    0.05       0
Bank Sta=205.17,216.1
XS Rating Curve= 0 ,0
Exp/Cntr(USF)=0,0
Exp/Cntr=0.3,0.1

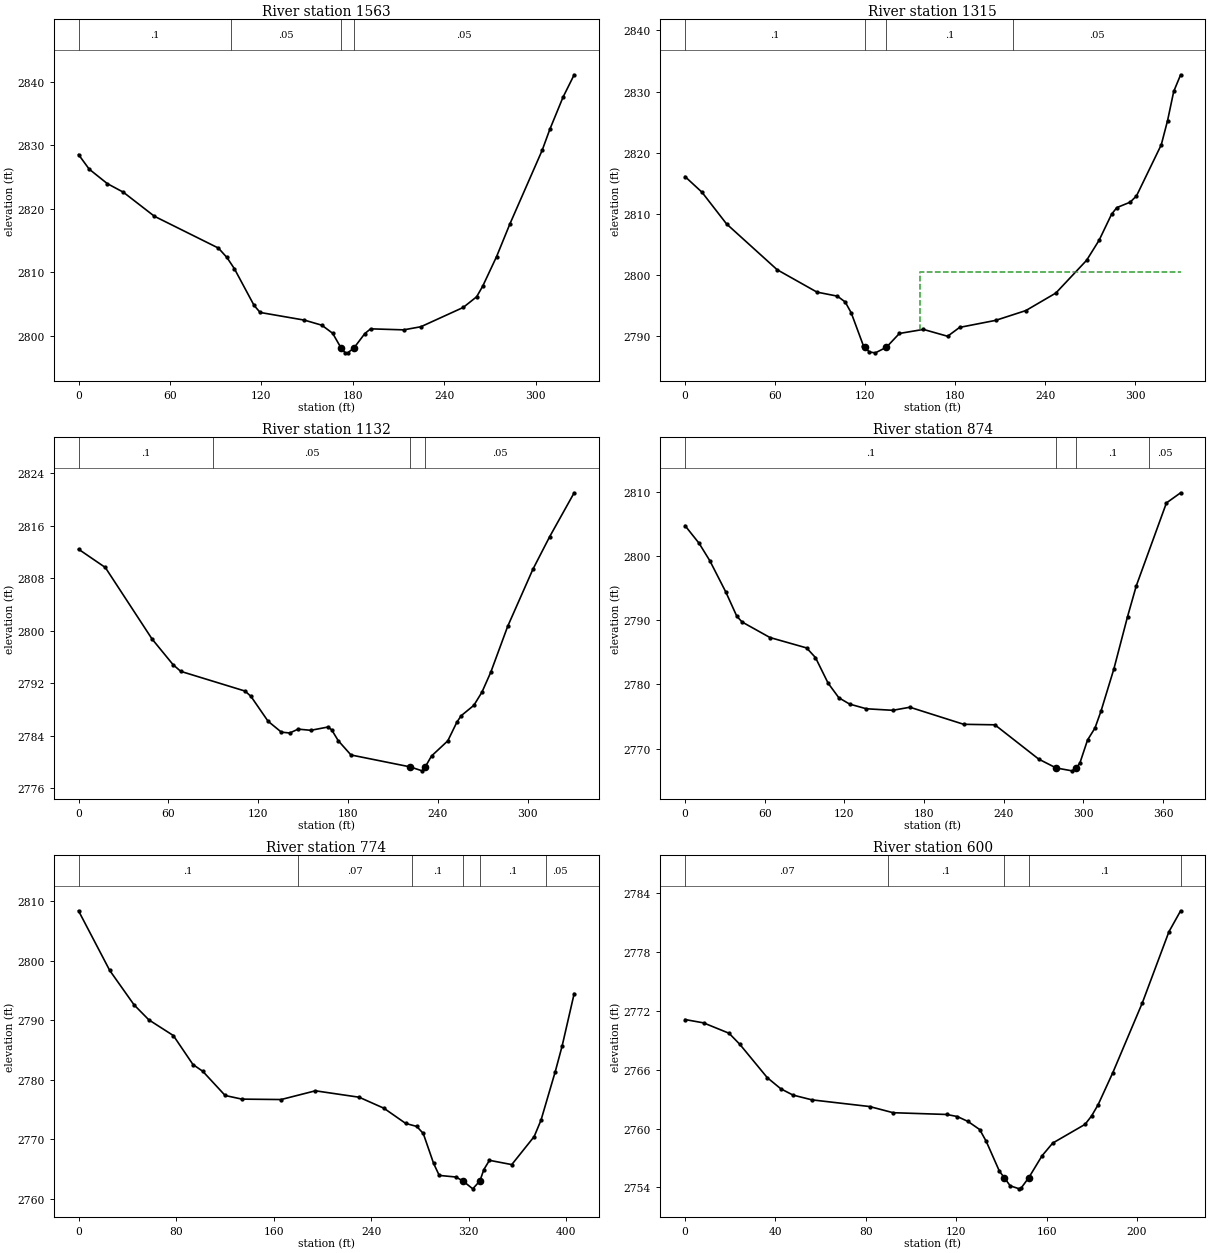
Type RM Length L Ch R = 1 ,1563    ,251.3,248,241.8
XS GIS Cut Line= 4
2382600.83982757666380.2490682232382530.83078287666457.581009059
2382425.46442576666560.0554245342382395.73265871666627.776202349
#Sta/Elev= 30
       0 2828.53       7 2826.23    18.9 2823.95    29.4  2822.6    49.8 2818.81
    91.8  2813.8    97.4 2812.32   102.3 2810.55   115.2 2804.78   119.2 2803.66
   148.3 2802.45   159.7 2801.65   166.8 2800.38   172.42798.032     175 2797.32
   176.6  2797.3  180.61 2798.02   187.9 2800.33   191.7 2801.08   213.4 2800.92
   224.7 2801.41   252.5 2804.45   261.3 2806.13   265.3 2807.81   274.4 2812.47
   283.1 2817.59   304.3  2829.2   309.3 2832.48     318 2837.57   325.3 2841.09
#Mann= 4, -1 ,  0
       0     0.1       0     100    0.05       0   172.4   0.045       0
  180.61    0.05       0
Bank Sta=172.4,180.61
XS Rating Curve= 0 ,0
Exp/Cntr(USF)=0,0
Exp/Cntr=0.3,0.1

Type RM Length L Ch R = 1 ,1315    ,177,183,184
XS GIS Cut Line= 4
2382352.42983257666266.6038372642382287.75129368 666326.94445253
2382277.32917347666490.2865273042382257.22934632666565.573405775
#Sta/Elev= 30
       0 2816.11    11.3 2813.55    27.7 2808.36    61.4 2800.87    87.9 2797.21
   101.5 2796.55   106.7  2795.6   110.7 2793.83   118.8 2788.46   119.82788.193
   122.8 2787.41   126.8 2787.28  134.152788.194   142.8 2790.45   158.8 2791.11
   174.9 2789.99   182.9 2791.44   206.9 2792.59     227 2794.19     247 2797.06
   267.5 2802.42   275.8 2805.69   284.1 2809.94   287.6 2811.03   296.5 2811.92
   300.7 2812.94   317.2  2821.3   321.4 2825.26   325.5 2830.03   330.1 2832.75
#Mann= 4, -1 ,  0
       0     0.1       0   119.8   0.045       0  134.15     0.1       0
  218.46    0.05       0
#XS Ineff= 2 , 0
                           156.5         2800.51
Permanent Ineff=
       F       F
Bank Sta=119.8,134.15
XS Rating Curve= 0 ,0
Exp/Cntr(USF)=0,0
Exp/Cntr=0.3,0.1

Type RM Length L Ch R = 1 ,1132    ,256.9,258.5,258.6
XS GIS Cut Line= 2
2382272.96937137666192.5566919442382036.48422943666424.268343105
#Sta/Elev= 30
       0 2812.46    17.9 2809.67    49.1 2798.77    63.2 2794.84    68.3 2793.83
   111.3 2790.82   115.2 2790.01   126.6 2786.23   135.5 2784.56   141.1 2784.43
   146.7 2785.02   155.2 2784.84   166.6 2785.34   169.1 2784.92   173.5 2783.26
     182 2781.08   221.6 2779.26   229.5 2778.66  231.58 2779.25   235.8 2780.92
   246.7 2783.24   252.7 2786.06   255.6 2787.06   264.1 2788.65   269.5 2790.66
   275.4  2793.7   286.7  2800.7   303.5 2809.38   314.7 2814.35   331.1 2821.06
#Mann= 4, -1 ,  0
       0     0.1       0      90    0.05       0   221.6   0.045       0
  231.58    0.05       0
Bank Sta=221.6,231.58
XS Rating Curve= 0 ,0
Exp/Cntr(USF)=0,0
Exp/Cntr=0.3,0.1

Type RM Length L Ch R = 1 ,874     ,97.5,100,101.2
XS GIS Cut Line= 3
2382214.62703004666142.9736922932381978.48352317666181.102317985
2381880.30290113666272.453945835
#Sta/Elev= 30
       0 2804.73    10.6 2801.98    18.7 2799.26    30.8 2794.36      39 2790.62
      43 2789.71      64 2787.29    91.6 2785.67    98.3 2784.16   107.8 2780.18
   115.9  2777.9     124 2776.92   136.6 2776.19   156.5 2775.95   169.4 2776.43
   209.9 2773.77   233.4 2773.69   266.4 2768.35  279.51 2766.97   291.5 2766.52
  294.86 2766.98   297.5 2767.78   303.2 2771.33   308.8 2773.19   313.4 2775.87
     323 2782.38   333.3 2790.53   339.9 2795.34   362.6 2808.26   373.3 2809.84
#Mann= 4, -1 ,  0
       0     0.1       0  279.51   0.045       0  294.86     0.1       0
   349.2    0.05       0
Bank Sta=279.51,294.86
XS Rating Curve= 0 ,0
Exp/Cntr(USF)=0,0
Exp/Cntr=0.3,0.1

Type RM Length L Ch R = 1 ,774     ,175.7,173.3,169.9
XS GIS Cut Line= 3
2382205.63083594666071.8096378172381952.82403918666095.079881264
2381819.52946862666169.590473599
#Sta/Elev= 30
       0 2808.43    25.6 2798.39    45.6 2792.59    57.7 2790.07    77.8 2787.43
    93.9 2782.55   101.9 2781.42   120.3 2777.34     134 2776.73   166.2 2776.66
   194.3 2778.13   230.2 2777.05   250.5  2775.2   268.4 2772.64   277.5 2772.13
   282.8 2770.95   291.3 2765.91   295.9 2763.89   309.6 2763.62   315.6 2762.92
   323.4 2761.63  329.272762.965   332.5 2764.87   337.1 2766.43   355.4 2765.71
   373.8 2770.43   379.4 2773.19   391.1 2781.37   396.7 2785.65   406.6 2794.49
#Mann= 6, -1 ,  0
       0     0.1       0     180    0.07       0  273.88     0.1       0
   315.6   0.045       0  329.27     0.1       0  383.88    0.05       0
Bank Sta=315.6,329.27
XS Rating Curve= 0 ,0
Exp/Cntr(USF)=0,0
Exp/Cntr=0.3,0.1

Type RM Length L Ch R = 1 ,600     ,131.7,129,128
XS GIS Cut Line= 4
2381898.92901462665896.410338411 2381819.2111163665972.142341811
 2381778.0235355 666039.902555382381756.76542929666061.160661598
#Sta/Elev= 30
       0 2771.13     8.2 2770.79    19.5 2769.73    24.3 2768.59    36.4  2765.2
    42.4 2764.06    47.8 2763.42    56.2 2762.93    81.7 2762.25    92.1 2761.62
   115.8 2761.44   120.5 2761.23   125.2 2760.73   130.4  2759.9   133.3 2758.69
   139.1 2755.66  141.252754.993   143.9 2754.16   147.9 2753.85   148.6 2753.89
  152.122754.993     158 2757.23   162.7 2758.52     177 2760.43   179.9 2761.29
   182.8 2762.44   189.3 2765.71   202.4 2772.86   214.1 2780.08   219.3 2782.23
#Mann= 5, -1 ,  0
       0    0.07       0      90     0.1       0  141.25   0.045       0
  152.12     0.1       0  219.25    0.05       0
Bank Sta=141.25,152.12
XS Rating Curve= 0 ,0
Exp/Cntr(USF)=0,0
Exp/Cntr=0.3,0.1

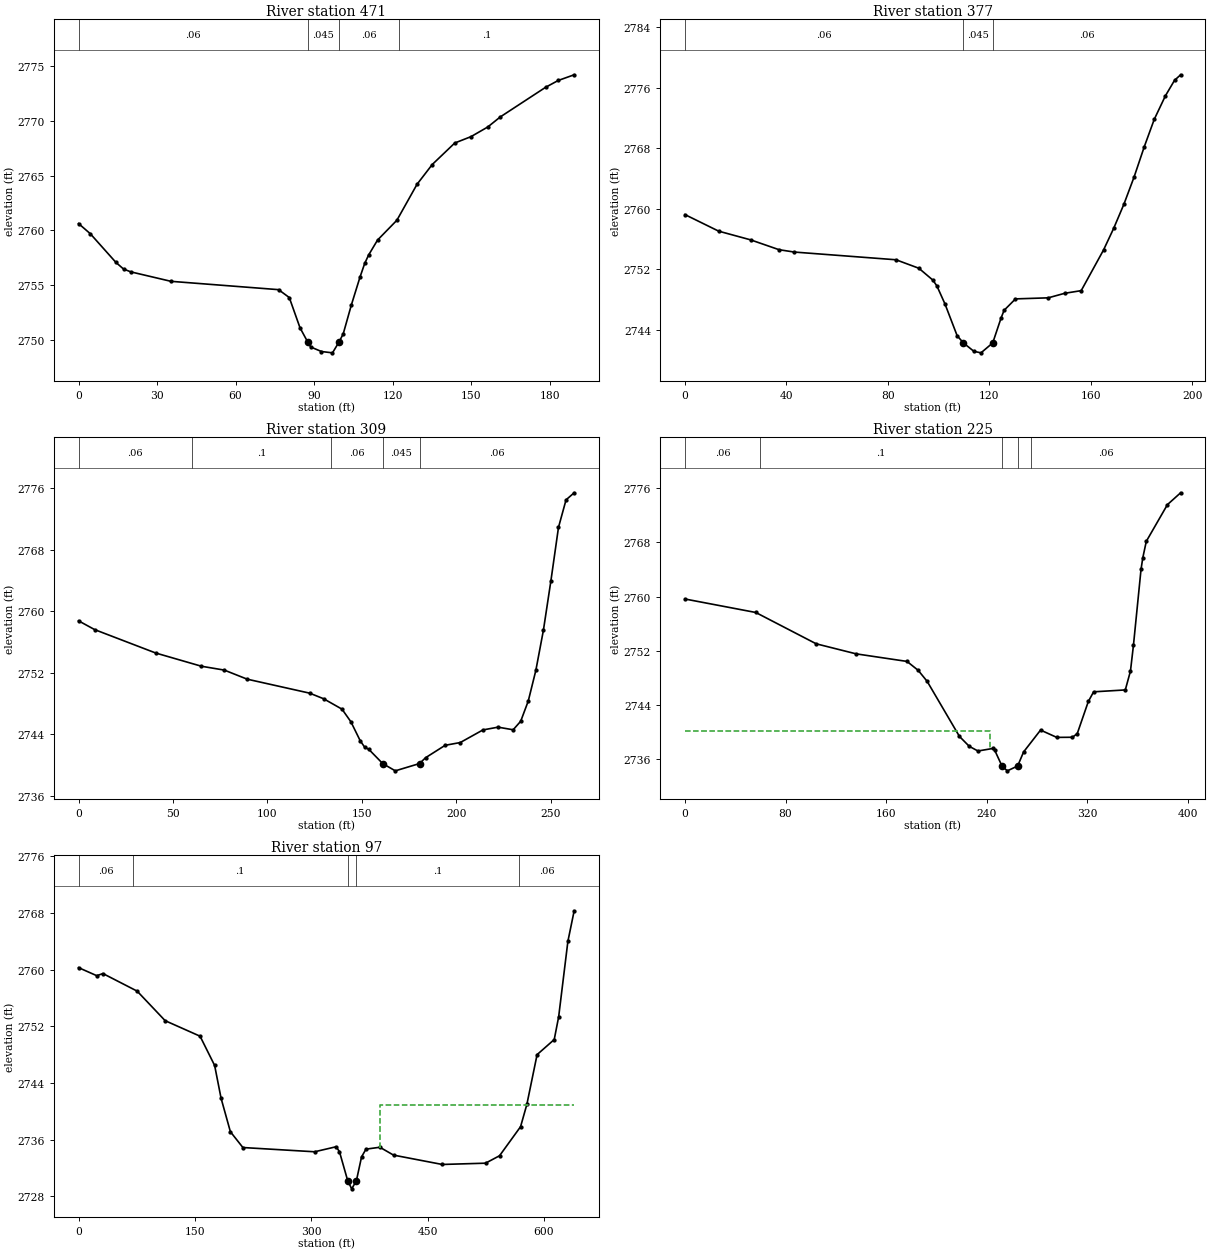
Type RM Length L Ch R = 1 ,471     ,89.2,94.8,98.3
XS GIS Cut Line= 4
2381733.52451079665854.4047962352381707.94546979665874.579975225
2381686.58844695 665963.494927472381722.11027925666018.266984601
#Sta/Elev= 30
       0 2760.63     4.5  2759.7    14.3 2757.08    17.2 2756.48      20 2756.22
    35.3 2755.36    76.4  2754.6    80.5 2753.88    84.6 2751.12   87.552749.822
    88.7 2749.37    92.8 2748.96      97 2748.84   99.482749.822   101.1 2750.57
   104.2  2753.2   107.5 2755.74   109.3 2756.99   110.8 2757.76   114.2 2759.12
   121.6 2760.93   129.3 2764.21   135.1 2766.01   143.7 2767.97   149.9 2768.55
   156.3 2769.43   161.1 2770.35   178.4 2773.05   183.2 2773.67   189.3 2774.19
#Mann= 4, -1 ,  0
       0    0.06       0   87.55   0.045       0   99.48    0.06       0
  122.58     0.1       0
Bank Sta=87.55,99.48
XS Rating Curve= 0 ,0
Exp/Cntr(USF)=0,0
Exp/Cntr=0.3,0.1

Type RM Length L Ch R = 1 ,377     ,68.1,67.8,75.4
XS GIS Cut Line= 6
2381712.77837402  665848.75021692381649.44826343665871.240469526
2381612.18243785665896.3458678072381595.31474838665905.368120314
2381571.38616565665912.4290135812381572.84490242665951.550695822
#Sta/Elev= 30
       0 2759.22    13.3 2757.03    25.9 2755.88    37.1 2754.58    43.1 2754.27
    83.2 2753.25    92.2 2752.13    97.7 2750.57    99.3  2749.8   102.5 2747.41
   107.3 2743.21  109.782742.256   113.9 2741.15   116.7 2740.95  121.322742.261
   124.6 2745.54   125.8 2746.57   130.3 2748.08   143.2 2748.22   149.7 2748.82
   156.2 2749.17     165 2754.54     169  2757.4     173 2760.56     177 2764.14
   181.1 2768.22     185 2771.81   189.4 2774.92     193 2776.97   195.4  2777.7
#Mann= 3, -1 ,  0
       0    0.06       0  109.78   0.045       0  121.32    0.06       0
Bank Sta=109.78,121.32
XS Rating Curve= 0 ,0
Exp/Cntr(USF)=0,0
Exp/Cntr=0.3,0.1

Type RM Length L Ch R = 1 ,309     ,87.1,84.1,74.5
XS GIS Cut Line= 6
2381700.74276673665829.4673457042381597.74961372665842.804588541
2381560.48378814665867.9099868222381543.61609867665876.932239329
2381519.68751594665883.9931325952381522.91147603665953.476655883
#Sta/Elev= 30
       0 2758.76     8.6 2757.61    40.9 2754.57    65.1 2752.85    77.2 2752.35
    89.3 2751.17   122.4 2749.35   129.8 2748.62   139.5 2747.27   144.2 2745.63
   149.1 2743.18   151.5 2742.32   153.7 2742.04  161.022740.199   167.7 2739.25
  180.542740.199   183.7 2740.95   194.1 2742.57   202.1 2742.93   214.1 2744.57
   222.1 2744.93   230.1 2744.59   234.1  2745.7   238.1 2748.33   242.1  2752.3
   246.1 2757.51   250.1 2763.99   254.1 2770.91   258.1 2774.49   262.4 2775.41
#Mann= 5, -1 ,  0
       0    0.06       0      60     0.1       0  133.85    0.06       0
  161.02   0.045       0  180.54    0.06       0
Bank Sta=161.02,180.54
XS Rating Curve= 0 ,0
Exp/Cntr(USF)=0,0
Exp/Cntr=0.3,0.1

Type RM Length L Ch R = 1 ,225     ,124.9,127.4,129.5
XS GIS Cut Line= 4
2381700.30690913665799.4930632082381485.63085819665814.318912651
2381451.85663702 665873.01964892 2381485.1675933665979.197155417
#Sta/Elev= 30
       0 2759.64    56.3 2757.65   104.4 2753.02   136.1 2751.54   176.6 2750.42
   185.5  2749.1   192.6 2747.48   218.3 2739.34   226.1 2737.88     233 2737.19
   244.7 2737.56   246.2 2737.36  252.14 2734.96   256.4 2734.26   264.6 2734.98
   269.3 2737.05   282.8 2740.28   295.7  2739.2   308.2 2739.22     312 2739.77
   320.8 2744.51     325 2745.93   350.2 2746.21   354.3    2749   356.7 2752.85
   362.7 2764.01   364.1 2765.72   366.9 2768.16   383.7 2773.58   394.2 2775.33
#Mann= 5, -1 ,  0
       0    0.06       0      60     0.1       0  252.14   0.045       0
   264.6     0.1       0  275.19    0.06       0
#XS Ineff= 2 , 0
           242.4 2740.11
Permanent Ineff=
       F       F
Bank Sta=252.14,264.6
XS Rating Curve= 0 ,0
Exp/Cntr(USF)=0,0
Exp/Cntr=0.3,0.1

Type RM Length L Ch R = 1 ,97      ,,,
XS GIS Cut Line= 4
2381707.62640678665787.8556341772381376.35693123665767.152137537
2381331.28691715665801.0080974862381436.58936682666028.548951621
#Sta/Elev= 30
       0 2760.27    23.5 2759.13    31.5 2759.43    75.6 2756.95   111.7 2752.78
   156.7 2750.59   175.5 2746.46   183.8 2741.83   195.8 2737.11   211.9 2734.88
   304.4 2734.28   332.1 2734.99   336.4  2734.3   347.12730.178   352.2 2729.05
   358.22730.175   364.9 2733.56   370.6 2734.65   388.5 2734.92   406.1 2733.81
   468.9 2732.49   524.7 2732.67   542.8 2733.72   569.9 2737.82     578 2740.96
   591.2 2747.99   613.3 2750.12     619 2753.32   630.9 2763.97     639 2768.29
#Mann= 5, -1 ,  0
       0    0.06       0      70     0.1       0   347.1   0.045       0
   358.2     0.1       0  568.29    0.06       0
#XS Ineff= 2 , 0
                          389.15         2740.87
Permanent Ineff=
       F       F
Bank Sta=347.1,358.2
XS Rating Curve= 0 ,0
Exp/Cntr(USF)=0,0
Exp/Cntr=0.3,0.1
LCMann Table=0

Chan Stop Cuts=-1
Use User Specified Reach Order=0
Composite Channel Slope=5